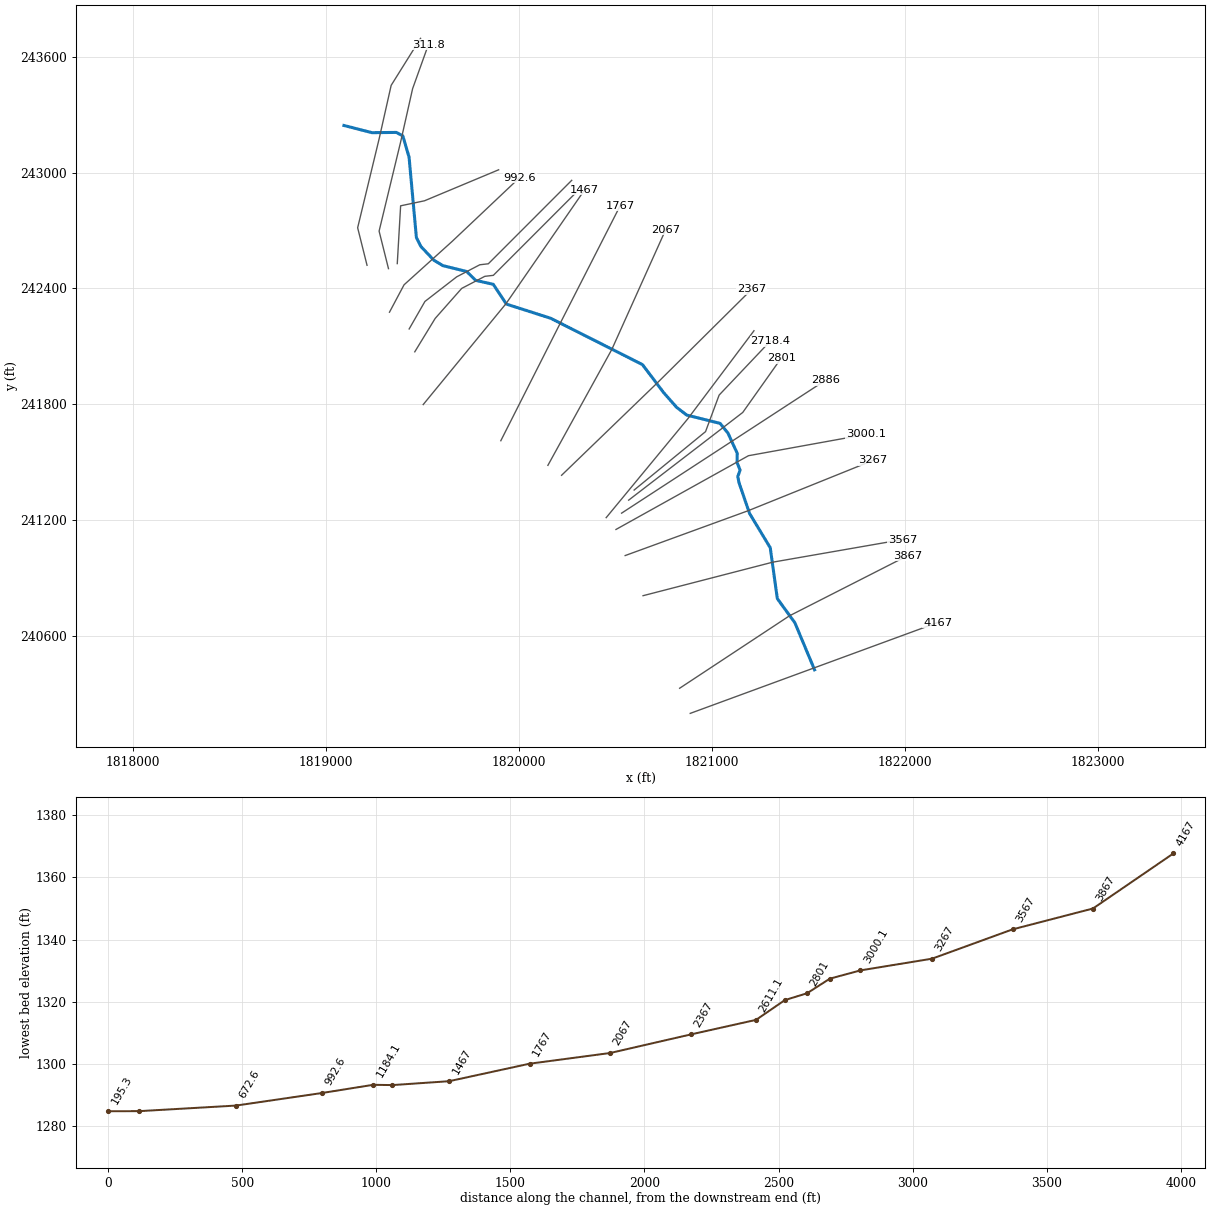
--- FORDSRN.prj (project) ---

Proj Title=FORDSRN
Current Plan=p01
Default Exp/Contr=0,0
English Units
Geom File=g01
Flow File=f01
Plan File=p01
BEGIN DESCRIPTION:
END DESCRIPTION:
DSS Export Rating Curves= 0
DSS Export Rating Curve Sorted= 0
DSS Export Volume Flow Curves= 0
DXF OffsetX= 0
DXF OffsetY= 0
DXF ScaleX= 0
DXF ScaleY= 0

--- FORDSRN.p01 (plan) ---

Plan Title=Floodplain
Program Version=4.00
Geom File=g01
Flow File=f01
K Sum by GR=0
Std Step Tol=0.01
Critical Tol=0.01
Num of Std Step Trials=20
Max Error Tol=0.3
Flow Tol Ratio=0.001
Split Flow NTrial=30
Split Flow Tol=0.02
Split Flow Ratio=0.02
Log Output Level=0
Friction Slope Method=1
Unsteady Friction Slope Method=2
Unsteady Bridges Friction Slope Method=1
Global Log Level=0
CheckData=False
Run HTab=0
Run UNet=0
Run PostProcess=0
UNET Theta=0
UNET Theta Warmup=0
UNET ZTol=0
UNET ZSATol=0
UNET MxIter=0
UNET MaxInSteps=0
UNET DtIC=0
UNET DtMin=0
UNET MaxCRTS=0
UNET WFStab=0
UNET SFStab=0
UNET WFX=0
UNET SFX=0
UNET DSS MLevel=0
UNET DZMax Abort=0
UNET Convert EG Bridges=0
UNET Use Existing IB Tables=0
UNET Froude Limit=0
UNET Froude Power=0
Write IC File=0
Echo Input=False
Echo Output=False
Write Detailed=0

--- FORDSRN.f01 (steady flow) ---

Flow Title=NFF Regression Equation
Program Version=4.00
Number of Profiles=1
Profile Names=P100yr
River Rch & RM=FORDSRN,Main      ,4167
503.0141
River Rch & RM=FORDSRN,Main      ,3000.1
535.4561
River Rch & RM=FORDSRN,Main      ,2611.1
613.6763
River Rch & RM=FORDSRN,Main      ,311.8
651.5961
River Rch & RM=FORDSRN,Main      ,195.3
653.0989
Boundary for River Rch & Prof#=FORDSRN,Main      ,1
Up Type=0
Dn Type=3
Dn Slope=0.005815

--- FORDSRN.g01 (geometry) ---

Geom Title=USGS 10m DEM
Program Version=4.10

River Reach=FORDSRN         ,Main
Reach XY= 30
     1821531.465      240423.768     1821429.772      240667.006
     1821338.555      240792.637     1821301.903      241056.122
     1821194.513      241234.457     1821139.967      241393.497
     1821133.729       241425.32     1821145.902      241458.478
     1821129.821      241497.599       1821130.9        241545.4
     1821082.695      241650.523     1821042.018      241700.542
     1820869.312      241743.537     1820817.133       241783.22
     1820750.704      241858.563     1820639.533       242005.23
     1820163.543      242245.413     1819934.814      242318.575
     1819866.771      242421.113      1819775.52      242441.561
     1819728.898      242487.543     1819605.895      242517.753
     1819558.499      242546.399     1819491.832      242617.233
     1819468.395      242663.587     1819430.524      243079.669
     1819398.082      243190.149     1819364.687      243208.124
     1819238.187      243206.816     1819092.914      243244.184

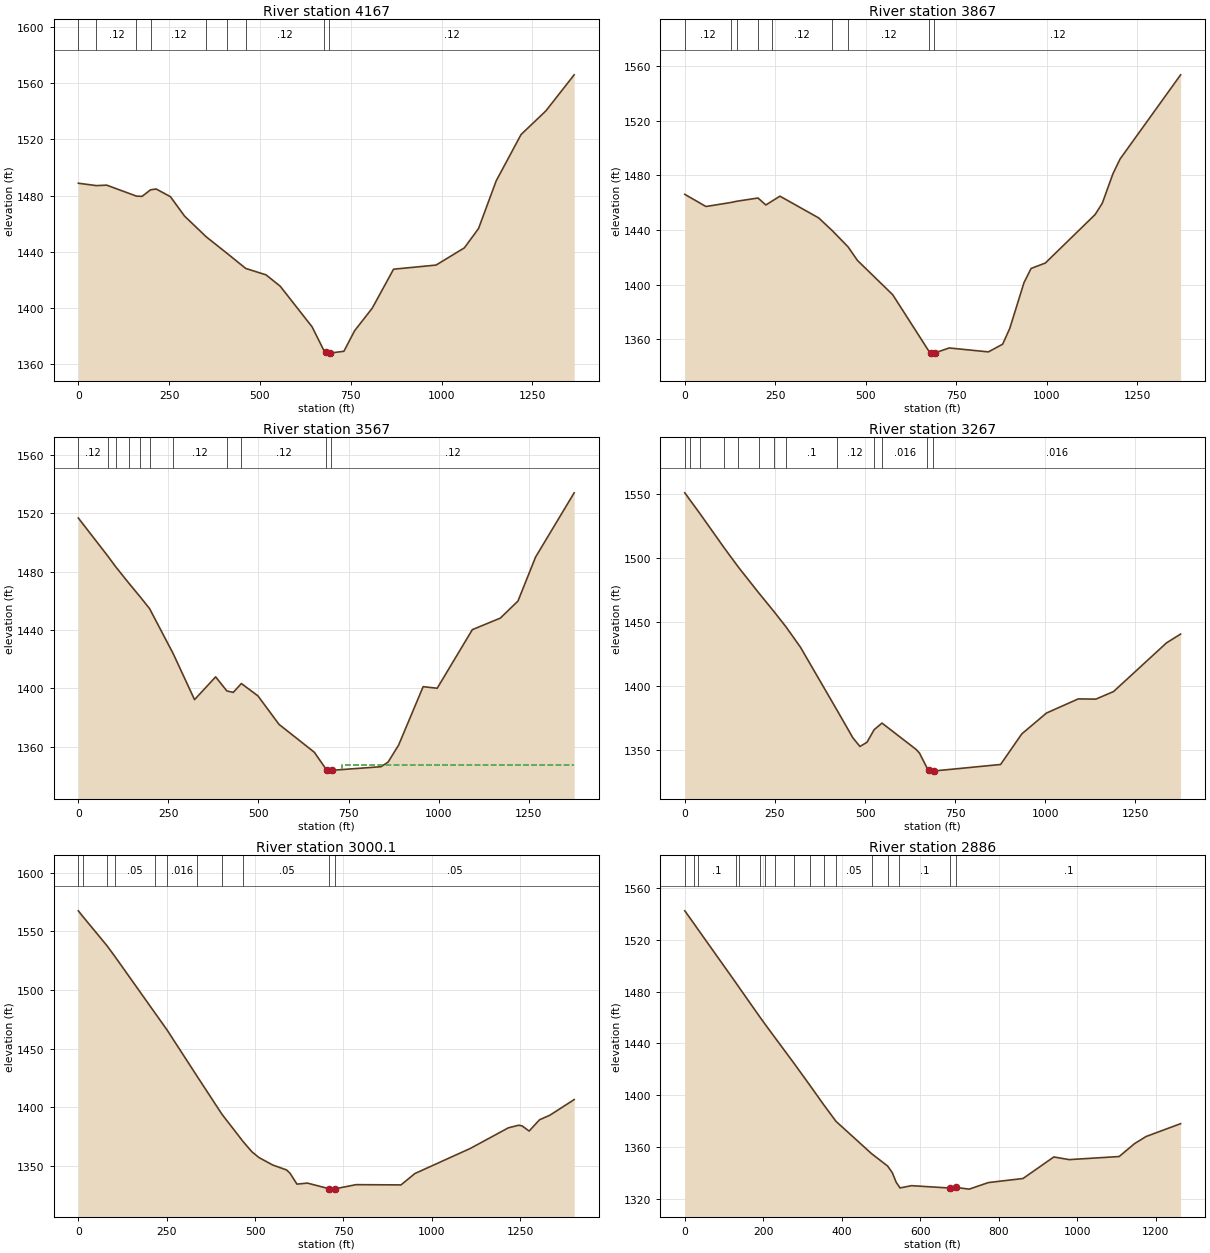
Type RM Length L Ch R = 1 ,4167    ,294.7,300,302.4
XS GIS Cut Line= 3
     1820887.327      240197.956     1821528.019      240433.156
     1822168.712      240668.356
#Sta/Elev= 30
       0 1488.79   49.921487.084      78 1487.43  160.031479.594   175.5 1479.42
  198.821484.096   214.5 1484.66   253.5  1479.2   292.5 1465.34  352.411450.518
  408.931438.908  460.841428.043   516.8 1423.47   555.8 1415.37   643.5 1386.42
     675  1370.1  680.72 1368.38     690 1367.72   692.2 1367.67   731.2    1369
   760.5 1383.61   809.2 1399.74   867.8  1427.5   984.8 1430.44  1062.8 1442.72
  1101.8 1456.51  1150.5 1490.55  1218.8 1523.49    1287 1540.31    1365 1566.06
#Mann= 9 ,-1 , 0
       0     .06       0   49.92     .12       0  160.03    .016       0
  198.82     .12       0  352.41     .06       0  408.93    .016       0
  460.84     .12       0     675    .045       0     690     .12       0
Bank Sta=680.72,692.2
XS Rating Curve= 0 ,0
Exp/Cntr=0.3,0.1

Type RM Length L Ch R = 1 ,3867    ,307.5,300,293.4
XS GIS Cut Line= 3
     1820832.466      240328.181     1821401.681      240703.582
     1822015.504      241015.886
#Sta/Elev= 30
       0 1466.19    58.4 1457.29  126.821460.192   145.11461.196  202.431463.502
     224 1458.39  240.021461.056     263 1464.85   370.2 1448.92  408.121439.499
  451.541427.682   477.3  1417.8   574.7 1392.74   674.4 1351.55   679.5 1350.42
   681.9 1349.97   689.4 1350.13   691.7 1350.18     731 1353.75   839.3 1350.88
   878.6  1356.5   898.3 1368.06   937.7 1401.59   957.3 1411.96   996.7 1415.92
  1134.4 1451.44  1154.1 1459.72  1183.6 1481.32  1203.3 1492.09  1370.6 1553.66
#Mann= 9 ,-1 , 0
       0     .12       0  126.82     .06       0   145.1    .016       0
  202.43     .06       0  240.02     .12       0  408.12    .016       0
  451.54     .12       0   674.4    .045       0   689.4     .12       0
Bank Sta=679.5,691.7
XS Rating Curve= 0 ,0
Exp/Cntr=0.3,0.1

Type RM Length L Ch R = 1 ,3567    ,297.9,300,304.8
XS GIS Cut Line= 3
     1820642.823      240807.702     1821314.588      240981.369
     1821986.753      241098.459
#Sta/Elev= 30
       0 1516.72   81.481490.762  103.281483.446  139.891472.163  172.421462.462
  197.621454.669  263.391423.727   322.5 1392.26   381.1 1407.86  412.151398.246
     430 1397.22  452.461403.291   498.4 1394.85     557 1375.31   654.8 1356.24
   686.4 1345.05  691.52 1343.77   693.8 1343.26   701.4 1343.69   703.6 1343.82
     840 1346.29   859.6 1349.41   888.8 1361.05     957 1401.14     996 1400.06
  1093.5 1440.21  1171.4 1448.15  1220.2 1459.83  1268.9  1489.9  1376.1 1533.98
#Mann= 11 ,-1 , 0
       0     .12       0   81.48     .06       0  103.28     .12       0
  139.89     .06       0  172.42    .016       0  197.62     .06       0
  263.39     .12       0  412.15    .016       0  452.46     .12       0
   686.4    .045       0   701.4     .12       0
#XS Ineff= 2 , 0
       0                   732.8       0 1347.16
Permanent Ineff=
       F       F
Bank Sta=691.52,703.6
XS Rating Curve= 0 ,0
Exp/Cntr=0.3,0.1

Type RM Length L Ch R = 1 ,3267    ,263.3,266.9,270.2
XS GIS Cut Line= 3
     1820550.244       241015.67      1821189.31      241248.725
     1821834.226      241508.676
#Sta/Elev= 30
       0 1551.19   14.651545.492   41.261535.278  109.011508.333   148.81493.117
   204.71473.212  246.691458.733  280.871446.477   320.7 1430.71  421.041382.082
   466.4 1359.83   485.9 1353.12   505.3 1356.34  525.341366.234  547.151371.359
   641.4 1350.89   651.1 1347.94   672.7 1335.99  676.15 1334.84   680.2 1333.85
   687.7 1333.91     690 1333.93   876.1 1339.04   934.9 1362.91  1003.4  1379.2
  1091.6 1390.26  1140.5 1390.08  1189.5 1395.99  1336.4    1434  1375.6  1440.9
#Mann= 13 ,-1 , 0
       0      .1       0   14.65     .12       0   41.26      .1       0
  109.01     .12       0   148.8     .08       0   204.7    .016       0
  246.69     .05       0  280.87      .1       0  421.04     .12       0
  525.34     .06       0  547.15    .016       0   672.7    .045       0
   687.7    .016       0
Bank Sta=676.15,690
XS Rating Curve= 0 ,0
Exp/Cntr=0.3,0.1

Type RM Length L Ch R = 1 ,3000.1  ,112.9,114.1,114.5
XS GIS Cut Line= 3
      1820502.55      241150.868     1821188.902      241532.988
     1821796.233      241643.087
#Sta/Elev= 30
       0 1567.57   13.141562.606   81.391537.701  103.64 1528.55  217.891479.988
  252.011465.497  335.181426.797  406.51 1393.92  466.741370.479     491    1362
   510.6 1357.12   549.9 1350.68   589.2 1346.44     599 1343.62   618.6 1334.37
   648.1 1335.23   710.6 1330.35   716.8 1330.09   725.6 1330.31   785.6  1333.9
   912.9 1333.69   952.1 1343.38  1108.9  1364.8  1216.6 1382.39    1246 1384.63
  1255.8 1384.02  1275.4 1379.65  1304.8 1389.27  1334.2 1393.18  1402.8  1406.5
#Mann= 11 ,-1 , 0
       0      .1       0   13.14     .05       0   81.39     .06       0
  103.64     .05       0  217.89     .06       0  252.01    .016       0
  335.18     .05       0  406.51      .1       0  466.74     .05       0
   710.6    .045       0   725.6     .05       0
Bank Sta=710.6,725.6
XS Rating Curve= 0 ,0
Exp/Cntr=0.3,0.1

Type RM Length L Ch R = 1 ,2886    ,83.2,85,86.7
XS GIS Cut Line= 2
     1820531.636      241235.392     1821590.663      241925.497
#Sta/Elev= 30
       0 1542.48   23.591532.492   33.341528.285  130.521486.771  138.86 1483.11
  191.631460.342  204.191455.082  230.921444.094  278.811424.492  320.371407.065
  353.681392.821  385.571379.767  476.221354.818  517.271345.213   529.1 1340.08
   538.9 1332.73  545.521329.771   548.7 1328.35   578.1  1330.1   676.3 1328.26
   691.3  1328.7   725.1 1327.43   774.1 1332.51   862.3 1335.65   940.7 1352.28
   979.9 1350.23  1107.3 1352.62  1146.4 1362.55  1175.8 1368.07    1264 1378.02
#Mann= 17 ,-1 , 0
       0     .12       0   23.59     .05       0   33.34      .1       0
  130.52     .12       0  138.86      .1       0  191.63     .05       0
  204.19      .1       0  230.92     .05       0  278.81    .016       0
  320.37     .05       0  353.68      .1       0  385.57     .05       0
  476.22      .1       0  517.27     .05       0  545.52      .1       0
   676.3    .045       0   691.3      .1       0
#XS Ineff= 2 , 0
       0   578.1                       0
Permanent Ineff=
       F       F
Bank Sta=676.3,691.3
XS Rating Curve= 0 ,0
Exp/Cntr=0.3,0.1

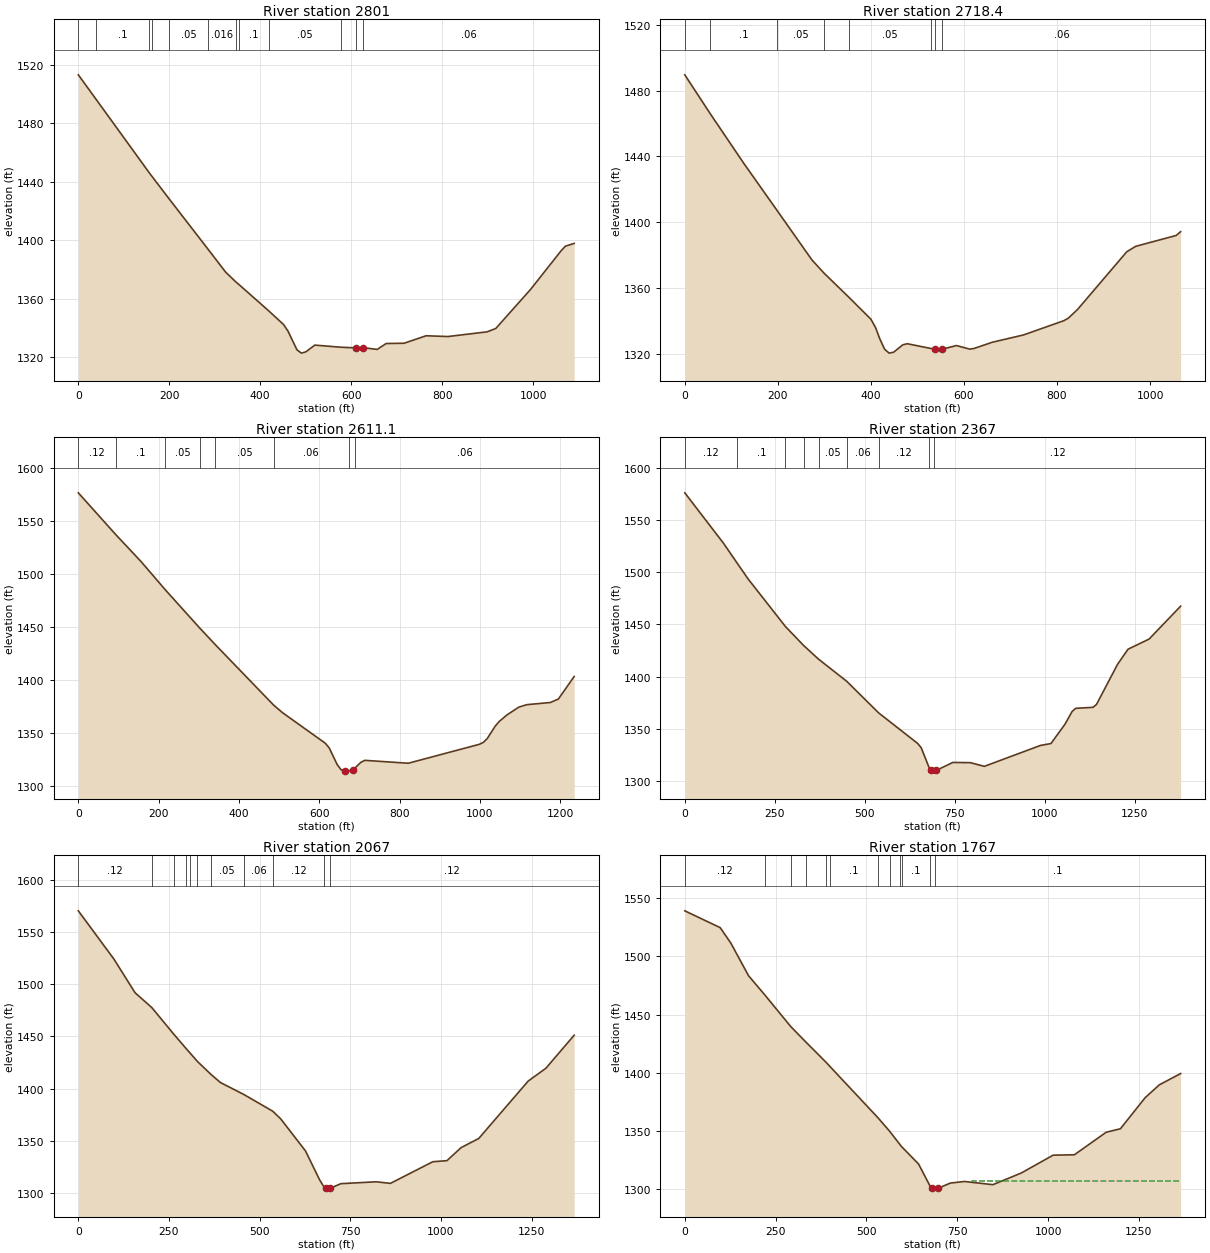
Type RM Length L Ch R = 1 ,2801    ,69.9,82.6,95.3
XS GIS Cut Line= 3
     1820568.311      241302.793     1821159.457       241757.22
     1821358.676       242038.47
#Sta/Elev= 30
       0 1513.26    39.11496.485  155.811446.277  162.241443.615  199.981428.216
  285.461393.798   323.8 1378.25  346.861371.353  352.581369.871  418.221351.806
   451.3 1342.32   461.1 1337.79   480.7 1325.02   490.5 1322.74   500.4 1323.64
     520 1328.23  576.531326.802   611.2  1326.3   626.2 1326.48   657.3 1325.29
     677 1329.32   716.2  1329.5   764.8 1334.63   812.6 1334.09   898.8 1337.31
     918 1339.62   994.6 1366.41  1061.6 1392.81  1071.1 1395.96  1090.3 1397.85
#Mann= 12 ,-1 , 0
       0     .12       0    39.1      .1       0  155.81     .12       0
  162.24      .1       0  199.98     .05       0  285.46    .016       0
  346.86     .05       0  352.58      .1       0  418.22     .05       0
  576.53     .06       0   611.2    .045       0   626.2     .06       0
#XS Ineff= 2 , 0
       0   529.8                       0
Permanent Ineff=
       F       F
Bank Sta=611.2,626.2
XS Rating Curve= 0 ,0
Exp/Cntr=0.3,0.1

Type RM Length L Ch R = 1 ,2718.4  ,114.4,107.4,100.7
XS GIS Cut Line= 4
     1820596.653      241355.094     1820966.662      241657.828
     1821036.974      241847.064      1821302.27      242126.999
#Sta/Elev= 30
       0 1489.53   53.921466.235   126.8 1435.78  198.831406.975   273.2 1377.15
  299.191369.127  352.871354.408     400 1341.14   409.8 1336.17   419.5 1328.97
   429.3    1323     439 1320.55   448.8  1321.1   468.3 1325.58   478.1 1326.26
     5291323.368   538.1 1322.81   553.1 1322.95   583.8 1325.15   612.7 1322.96
   622.3 1323.43   660.7 1327.14   728.2 1331.61   814.9 1340.27   824.6 1341.88
   843.9    1347   949.9 1382.11   969.2 1385.41    1056 1391.99  1065.6  1394.3
#Mann= 8 ,-1 , 0
       0     .12       0   53.92      .1       0  198.83     .05       0
  299.19    .016       0  352.87     .05       0     529     .06       0
   538.1    .045       0   553.1     .06       0
#XS Ineff= 2 , 0
       0   478.1 1326.26   583.8       0 1325.15
Permanent Ineff=
       F       F
Bank Sta=538.1,553.1
XS Rating Curve= 0 ,0
Exp/Cntr=0.3,0.1

Type RM Length L Ch R = 1 ,2611.1  ,247.4,244.1,241.3
XS GIS Cut Line= 3
     1820451.855      241212.101     1820874.666      241724.308
     1821217.548      242180.471
#Sta/Elev= 30
       0 1576.91   92.671537.698   156.3    1512  216.551485.392  302.271449.295
  341.251433.524  486.351376.539   507.9 1369.56   615.3 1340.46   625.1 1335.91
   644.6 1320.42   654.4 1315.48   664.2  1314.2   673.8 1314.57   683.8 1315.61
   688.8 1317.11   703.5  1322.5   713.4 1324.38   821.6 1321.63   998.7 1339.52
  1008.5 1341.28  1018.4 1344.96    1038 1356.56  1047.9 1360.98  1067.6 1367.29
  1097.1 1374.64  1116.8 1376.91  1175.8 1379.01  1195.5 1382.25  1234.8 1403.52
#Mann= 8 ,-1 , 0
       0     .12       0   92.67      .1       0  216.55     .05       0
  302.27    .016       0  341.25     .05       0  486.35     .06       0
   673.8    .045       0   688.8     .06       0
Bank Sta=664.2,683.8
XS Rating Curve= 0 ,0
Exp/Cntr=0.3,0.1

Type RM Length L Ch R = 1 ,2367    ,293,300,308
XS GIS Cut Line= 3
     1820220.739      241431.582     1820714.534       241908.32
     1821205.703      242395.051
#Sta/Elev= 30
       0 1576.02   107.9 1527.59  146.281508.288   176.5  1493.3  279.63    1448
  330.291429.805  371.81  1416.7  449.981395.534  538.841365.231   647.2    1336
     657  1331.9   678.9 1312.94  683.62 1310.67   693.9 1309.51   696.1  1309.5
  699.26 1310.23   744.8 1317.82   793.5  1317.6   832.5 1314.08   988.3 1334.09
  1017.5  1335.9  1056.5 1354.41    1076 1366.42  1085.7 1369.61  1134.4 1370.61
  1144.1 1373.36  1202.6 1411.77  1231.8 1426.27  1290.2 1435.94  1377.9 1467.46
#Mann= 9 ,-1 , 0
       0     .12       0  146.28      .1       0  279.63     .05       0
  330.29    .016       0  371.81     .05       0  449.98     .06       0
  538.84     .12       0   678.9    .045       0   693.9     .12       0
Bank Sta=683.62,699.26
XS Rating Curve= 0 ,0
Exp/Cntr=0.3,0.1

Type RM Length L Ch R = 1 ,2067    ,299.1,300,298.9
XS GIS Cut Line= 3
     1820149.811      241483.062     1820480.728      242083.108
     1820760.504      242705.097
#Sta/Elev= 30
       0 1570.54    97.9 1524.38   156.6 1491.89  202.431477.814   264.3 1451.76
  296.451438.743  307.181434.469   328.61425.984  364.541414.016   391.6 1405.86
  456.98 1394.23  536.061378.306     558    1371   626.5 1340.16   665.7 1312.24
   677.7 1305.55  682.29 1304.35   685.2 1303.55   692.7 1304.26     695 1304.48
   724.2 1308.79   821.6 1310.59   860.6 1309.06   977.5 1329.83  1016.5 1330.87
  1055.5 1343.36  1104.2 1352.13  1240.6 1407.24  1289.3  1419.5  1367.3  1451.2
#Mann= 11 ,-1 , 0
       0     .12       0  202.43      .1       0   264.3     .05       0
  296.45     .06       0  307.18     .05       0   328.6    .016       0
  364.54     .05       0  456.98     .06       0  536.06     .12       0
   677.7    .045       0   692.7     .12       0
Bank Sta=682.29,695
XS Rating Curve= 0 ,0
Exp/Cntr=0.3,0.1

Type RM Length L Ch R = 1 ,1767    ,305.4,300,296.7
XS GIS Cut Line= 3
     1819905.894      241610.679     1820213.894      242219.735
     1820523.957      242827.737
#Sta/Elev= 30
       0 1539.09    97.5 1524.64   126.8 1511.38   175.5 1483.36  220.791466.704
  291.781439.689  333.581426.349  389.841408.755  399.341405.526  530.861361.734
  563.741349.881  591.461338.756  596.631336.687   643.5 1321.72     675 1302.86
  680.03 1301.05   682.5 1300.12     690 1300.12  696.98  1300.8   731.2 1305.34
   770.2 1306.68   848.2 1303.94   926.2 1313.93    1014 1329.28  1072.5 1329.62
  1160.2 1348.98  1199.2 1351.94  1267.5  1378.7  1306.5  1389.7    1365 1399.36
#Mann= 12 ,-1 , 0
       0     .12       0  220.79      .1       0  291.78     .05       0
  333.58    .016       0  389.84     .05       0  399.34      .1       0
  530.86     .05       0  563.74      .1       0  591.46     .05       0
  596.63      .1       0     675    .045       0     690      .1       0
#XS Ineff= 2 , 0
       0                   789.8       0 1306.86
Permanent Ineff=
       F       F
Bank Sta=680.03,696.98
XS Rating Curve= 0 ,0
Exp/Cntr=0.3,0.1

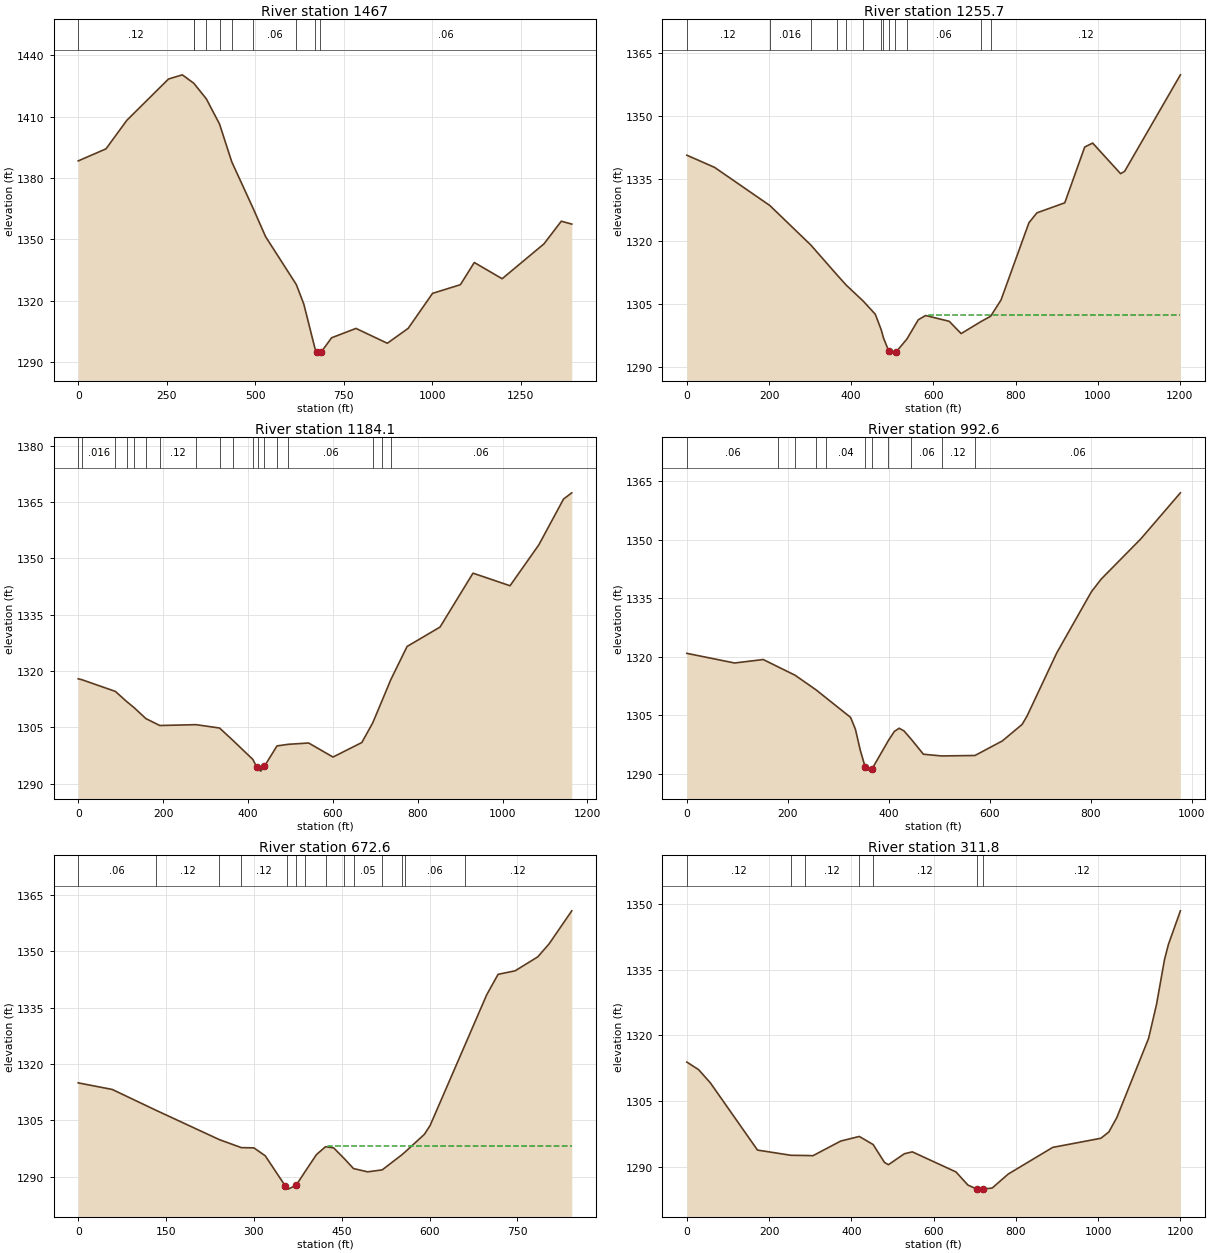
Type RM Length L Ch R = 1 ,1467    ,223.9,211.3,186.2
XS GIS Cut Line= 3
     1819503.742      241798.034     1819932.727      242320.755
     1820340.401      242911.024
#Sta/Elev= 30
       0 1388.38    78.4 1394.26   137.2 1408.19   254.8 1428.36     294 1430.42
  326.321426.304  327.091426.147  361.691418.708     3991406.401  433.611387.905
  493.281365.442   529.2 1351.35  615.941327.955     637 1318.45   668.7 1296.67
  673.97 1295.18   676.2  1294.5   683.7 1294.91     686 1295.03   715.5    1302
   784.3 1306.57   872.8 1299.32   931.7  1306.6  1000.5 1323.69  1079.1 1327.92
  1118.4 1338.76    1197 1330.84    1315 1347.84  1364.1 1358.94  1393.6 1357.52
#Mann= 10 ,-1 , 0
       0     .12       0  326.32     .06       0  327.09     .08       0
  361.69    .016       0     399     .05       0  433.61     .12       0
  493.28     .06       0  615.94     .12       0   668.7    .045       0
   683.7     .06       0
Bank Sta=673.97,686
XS Rating Curve= 0 ,0
Exp/Cntr=0.3,0.1

Type RM Length L Ch R = 1 ,1255.7  ,73.5,71.6,83.9
XS GIS Cut Line= 6
     1819460.082      242071.335     1819565.725      242244.338
     1819703.225      242399.894     1819822.947      242462.434
       1819867.2      242467.602     1820299.232       242899.98
#Sta/Elev= 30
       0 1340.61    67.6 1337.69     2021328.571  301.71 1319.12  365.96 1311.92
  388.031309.506  429.111305.717   458.6 1302.56  472.91 1298.88  478.591296.876
   491.8 1293.66   497.2 1293.25   506.8 1293.37  509.99 1293.62  535.511296.617
   563.2 1301.22     581 1302.25   638.5 1300.87   667.6 1297.93  716.661300.849
  739.38 1302.08   764.6 1305.96   832.5 1324.43   851.9 1326.81   919.8 1329.22
   968.3 1342.56   987.7 1343.51  1055.6 1336.19  1065.4 1336.74  1201.2 1359.84
#Mann= 13 ,-1 , 0
       0     .12       0     202    .016       0  301.71     .06       0
  365.96     .12       0  388.03    .016       0  429.11     .06       0
  472.91      .1       0  478.59     .05       0   491.8    .045       0
   506.8     .05       0  535.51     .06       0  716.66      .1       0
  739.38     .12       0
#XS Ineff= 2 , 0
       0                     590       0  1302.3
Permanent Ineff=
       F       F
Bank Sta=491.8,509.99
XS Rating Curve= 0 ,0
Exp/Cntr=0.3,0.1

Type RM Length L Ch R = 1 ,1184.1  ,180.5,191.5,197.7
XS GIS Cut Line= 6
     1819431.002      242189.824       1819512.6      242332.185
     1819677.183      242459.789     1819796.906       242522.33
     1819841.159      242527.498      1820273.19      242959.876
#Sta/Elev= 30
       0 1317.92     8.11317.718   87.551314.579  114.46 1311.85  132.291310.191
  159.561307.328  192.251305.491   277.61305.718  333.121304.821  364.081301.588
  411.521296.463   420.6 1294.46   423.8 1294.09   430.2 1293.34   438.8 1294.63
   468.51300.058  495.051300.486   543.1 1300.83   600.5 1297.09   668.4 1300.96
  693.921306.154  716.771312.295  736.421317.643   775.1 1326.55   852.7 1331.71
   930.4 1346.07  1017.7 1342.72  1085.6 1353.62  1143.8 1365.81  1163.2 1367.47
#Mann= 18 ,-1 , 0
       0     .12       0     8.1    .016       0   87.55     .12       0
  114.46    .016       0  132.29     .12       0  159.56     .06       0
  192.25     .12       0   277.6    .016       0  333.12     .08       0
  364.08     .06       0  411.52      .1       0   423.8    .045       0
   438.8      .1       0   468.5     .05       0  495.05     .06       0
  693.92      .1       0  716.77     .05       0  736.42     .06       0
#XS Ineff= 2 , 0
       0                   543.1       0 1300.83
Permanent Ineff=
       F       F
Bank Sta=420.6,438.8
XS Rating Curve= 0 ,0
Exp/Cntr=0.3,0.1

Type RM Length L Ch R = 1 ,992.6   ,331.9,320.1,308.1
XS GIS Cut Line= 4
     1819329.006       242276.63     1819404.527      242418.557
     1819654.527      242644.251     1820003.485      242974.112
#Sta/Elev= 30
       0 1320.87    94.6  1318.4   151.3 1319.29  181.251317.377  214.41 1315.27
  256.12 1311.51  275.751309.477   324.4 1304.47     334 1301.42   343.6 1296.06
   352.2 1292.23   353.2 1291.78   362.8  1290.7   367.2 1291.34  399.271298.537
     411 1300.85   420.6 1301.69   430.2 1301.01  444.74 1298.84   468.7 1295.03
  504.53 1294.59  570.811294.704     625 1298.43   664.2 1302.66     674 1304.81
   732.8 1320.98   801.4 1336.63     821 1339.91   899.4  1350.2   977.8 1361.99
#Mann= 11 ,-1 , 0
       0     .06       0  181.25     .12       0  214.41    .016       0
  256.12     .06       0  275.75     .04       0   352.2    .045       0
   367.2     .04       0  399.27     .12       0  444.74     .06       0
  504.53     .12       0  570.81     .06       0
#XS Ineff= 2 , 0
       0                   420.6       0 1301.69
Permanent Ineff=
       F       F
Bank Sta=353.2,367.2
XS Rating Curve= 0 ,0
Exp/Cntr=0.3,0.1

Type RM Length L Ch R = 1 ,672.6   ,326.8,360.7,387.9
XS GIS Cut Line= 4
      1819369.37      242528.366     1819386.732      242827.845
      1819510.43      242853.887     1819894.544      243014.477
#Sta/Elev= 30
       0 1314.95    58.1  1313.2  133.161307.631  241.061299.841  278.571297.715
     300 1297.65   319.4 1295.53  353.14 1287.61     357 1286.91   358.3 1286.67
     372 1287.68  387.651291.397   406.9 1295.89  422.311297.953   436.1 1297.65
  454.551294.749  470.061292.144   494.2 1291.27  519.031291.792  552.391295.782
  557.47 1296.47     591 1301.24   600.7 1303.57  659.811324.833   697.5 1338.41
   716.9 1343.84   745.9 1344.77   784.6 1348.48     804 1351.95   842.7 1360.74
#Mann= 14 ,-1 , 0
       0     .06       0  133.16     .12       0  241.06     .06       0
  278.57     .12       0     357    .045       0     372     .12       0
  387.65     .06       0  422.31    .016       0  454.55      .1       0
  470.06     .05       0  519.03     .06       0  552.39     .12       0
  557.47     .06       0  659.81     .12       0
#XS Ineff= 2 , 0
       0                   426.4       0 1298.21
Permanent Ineff=
       F       F
Bank Sta=353.14,372
XS Rating Curve= 0 ,0
Exp/Cntr=0.3,0.1

Type RM Length L Ch R = 1 ,311.8   ,123.3,116.6,114.9
XS GIS Cut Line= 5
     1819323.798      242502.324     1819275.186      242696.769
     1819386.298      243156.838     1819448.798      243434.616
     1819530.395      243662.046
#Sta/Elev= 30
       0 1313.91    28.6 1312.18    57.3 1309.15   171.8  1293.8  253.25 1292.61
  287.561292.569   306.7 1292.52   374.3 1295.87  419.341296.917  452.981295.069
   480.5 1290.99   490.2 1290.46   528.8 1292.96   548.2  1293.4   654.4 1288.81
   683.5  1285.8   705.1  1284.9     713 1284.88   720.1 1284.89   742.4 1285.13
   781.7 1288.34   889.7 1294.42  1006.8  1296.5  1026.1 1297.94  1045.4 1301.21
  1122.8 1319.34  1142.1 1327.12  1161.4 1337.31  1171.1 1340.84  1200.1 1348.47
#Mann= 7 ,-1 , 0
       0     .12       0  253.25     .06       0  287.56     .12       0
  419.34     .06       0  452.98     .12       0   705.1    .045       0
   720.1     .12       0
Bank Sta=705.1,720.1
XS Rating Curve= 0 ,0
Exp/Cntr=0.3,0.1

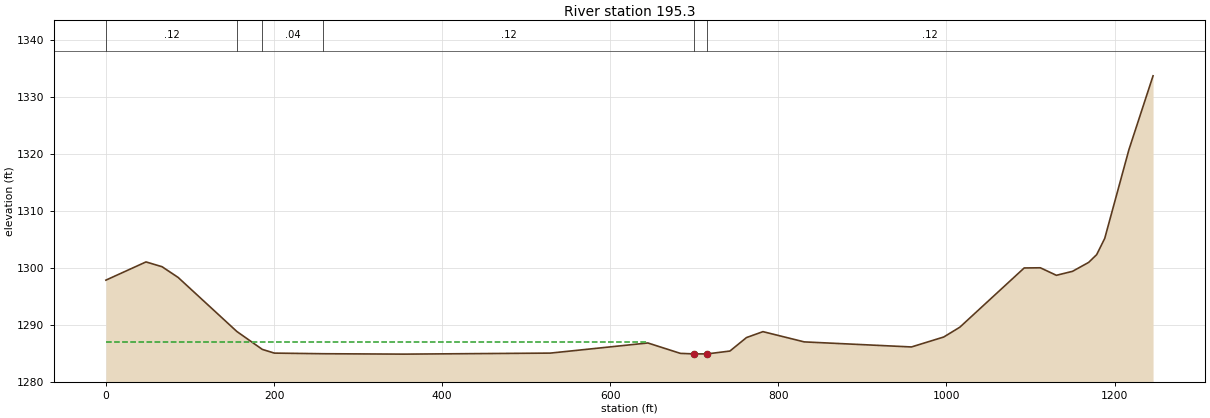
Type RM Length L Ch R = 1 ,195.3   ,193.8,195.3,196.4
XS GIS Cut Line= 5
     1819212.686      242519.685     1819164.075       242714.13
     1819275.186      243174.199     1819337.686      243451.977
      1819490.03      243695.611
#Sta/Elev= 30
       0 1297.85    47.7 1301.05    66.8 1300.21    85.9 1298.33  155.821288.826
  186.081285.681   200.4 1285.03  258.821284.919     355 1284.85   528.8 1285.03
   644.8 1286.81   683.5 1284.98   700.2 1284.89   715.2 1284.89   742.4 1285.39
   762.1 1287.76   781.7  1288.8   830.8    1287   958.4 1286.11   996.8 1287.86
  1015.9 1289.58  1092.5 1299.99  1111.7 1300.02  1130.8  1298.7    1150  1299.4
  1169.2 1300.97  1178.7 1302.33  1188.3 1305.18  1217.1 1320.78  1245.8 1333.75
#Mann= 6 ,-1 , 0
       0     .12       0  155.82    .016       0  186.08     .04       0
  258.82     .12       0   700.2    .045       0   715.2     .12       0
#XS Ineff= 2 , 0
       0   644.8    1287   781.7       0  1288.8
Permanent Ineff=
       F       F
Bank Sta=700.2,715.2
XS Rating Curve= 0 ,0
Exp/Cntr=0.3,0.1

Chan Stop Cuts=-1
Use User Specified Reach Order=0
Composite Channel Slope=5